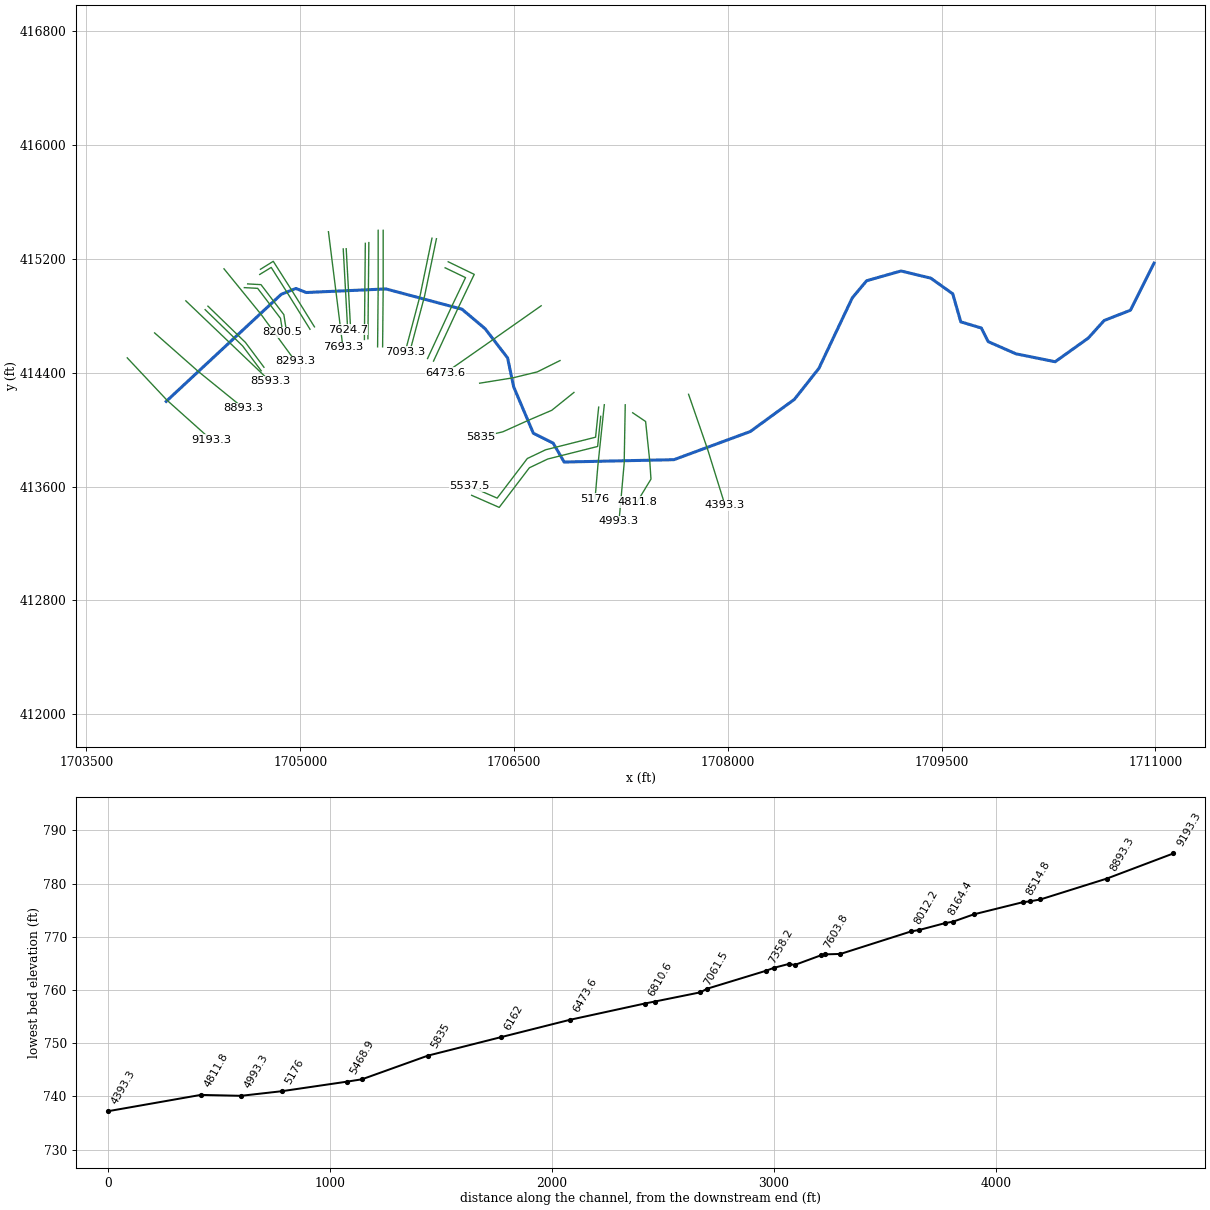
--- DODSONFK.prj (project) ---

Proj Title=DODSONFK
Current Plan=p01
Default Exp/Contr=0,0
English Units
Geom File=g01
Flow File=f01
Plan File=p01
BEGIN DESCRIPTION:
END DESCRIPTION:
DSS File=dss
DSS Export Rating Curves= 0
DSS Export Rating Curve Sorted= 0
DSS Export Volume Flow Curves= 0
DXF OffsetX= 0
DXF OffsetY= 0
DXF ScaleX= 0
DXF ScaleY= 0

--- DODSONFK.p01 (plan) ---

Plan Title=Floodplain
Program Version=4.10
Short Identifier=Floodplain
Geom File=g01
Flow File=f01
Subcritical Flow
K Sum by GR= 0
Std Step Tol= 0.01
Critical Tol= 0.01
Num of Std Step Trials= 20
Max Error Tol= 0.3
Flow Tol Ratio= 0.001
Split Flow NTrial= 30
Split Flow Tol= 0.02
Split Flow Ratio= 0.02
Log Output Level= 0
Friction Slope Method= 1
Unsteady Friction Slope Method= 2
Unsteady Bridges Friction Slope Method= 1
Parabolic Critical Depth
Global Vel Dist= 0 , 0 , 0
Global Log Level= 0
CheckData=True
Encroach Param=-1 ,0,0, 0
Run HTab= 0
Run UNet= 0
Run PostProcess= 0
Run WQNet= 0
UNET Theta= 0
UNET Theta Warmup= 0
UNET ZTol= 0
UNET ZSATol= 0
UNET MxIter= 0
UNET MaxInSteps= 0
UNET DtIC= 0
UNET DtMin= 0
UNET MaxCRTS= 0
UNET WFStab= 0
UNET SFStab= 0
UNET WFX= 1
UNET SFX= 1
UNET DSS MLevel= 1
UNET DZMax Abort= 0
UNET Convert EG Bridges= 0
UNET Use Existing IB Tables= 0
UNET Froude Reduction=False
UNET Froude Limit= 0
UNET Froude Power= 0
UNET Time Slicing=0,0, 5
UNET Junction Losses=0
DSS File=dss
Write IC File= 0
Write IC File at Sim End=0
Echo Input=False
Echo Parameters=False
Echo Output=False
Write Detailed= 0
WQ AD Non Conservative
WQ ULTIMATE=-1
WQ Max Comp Step=1HOUR
WQ Output Interval=15MIN
WQ Output Selected Increments= 0
WQ Output face flow=0
WQ Output face velocity=0
WQ Output face area=0
WQ Output face dispersion=0
WQ Output cell volume=0
WQ Output cell surface area=0
WQ Output cell continuity=0
WQ Output cumulative cell continuity=0
WQ Output face conc=0
WQ Output face dconc_dx=0
WQ Output face courant=0
WQ Output face peclet=0
WQ Output face adv mass=0
WQ Output face disp mass=0
WQ Output cell mass=0
WQ Output cell source sink temp=0
WQ Output cell source sink nsm=0
WQ Output MaxMinRange=-1
WQ Daily Max Min Mean=-1
WQ Daily Range=0
WQ Daily Time=0
WQ Create Restart=0
WQ Fixed Restart=0
WQ System Summary=0
WQ Use Fixed Temperature=0
Sorting and Armoring Iterations= 10
XS Update Threshold= 0.02
Hydraulics Update Threshold= 0.02
Energy Slope Method= 1
Volume Change Method= 0
XS Weighting Method= 0
Number of US Weighted Cross Sections= 1
Number of DS Weighted Cross Sections= 1
Upstream XS Weight=0.25
Main XS Weight=0.5
Downstream XS Weight=0.25
Number of DS XS's Weighted with US Boundary= 1
Upstream Boundary Weight= 1
Weight of XSs Associated with US Boundary= 0
Number of US XS's Weighted with DS Boundary= 1
Downstream Boundary Weight= 0.5
Weight of XSs Associated with DS Boundary= 0.5
Sediment Output Level= 4
Mass or Volume Output= 0
Output Increment Type= 1
Profile and TS Output Increment= 10
XS Output Flag= 0
XS Output Increment= 10
Disregard all LS=0
Disregard all Conn=0
Disregard all Breaches=0
Disregard all Pumps=0

--- DODSONFK.f01 (steady flow) ---

Flow Title=NFF Regression Equation
Program Version=4.10
Number of Profiles= 1
Profile Names=P100yr
River Rch & RM=DODSONFK,Main            ,9193.3
909.9776
River Rch & RM=DODSONFK,Main            ,7693.3
 1164.35
River Rch & RM=DODSONFK,Main            ,6162
1259.587
River Rch & RM=DODSONFK,Main            ,4993.3
1858.236
River Rch & RM=DODSONFK,Main            ,3193.3
1976.514
Boundary for River Rch & Prof#=DODSONFK,Main            , 1
Up Type= 0
Dn Type= 3
Dn Slope=0.00342
DSS Import GetInterval= 0
DSS Import GetPeak= 0
DSS Import FillOption= 0

--- DODSONFK.g01 (geometry) ---

Geom Title=USGS 10m DEM
Program Version=4.10

River Reach=DODSONFK        ,Main
Reach XY= 30
     1704060.067      414198.868     1704867.045      414951.721
     1704969.823      414992.953     1705041.871      414964.307
     1705601.767      414989.481     1706134.927       414847.12
     1706297.253      414709.967     1706455.066      414504.325
       1706497.6        414301.2     1706635.621      413975.245
      1706774.51      413905.801     1706851.767      413772.554
     1707621.906      413789.047     1708157.496      413986.963
     1708467.045      414213.092      1708638.92      414430.974
     1708873.295      414926.894     1708973.816       415047.12
     1709215.135      415115.696     1709423.469      415065.349
     1709577.982      414955.106     1709634.406      414758.057
     1709778.503      414714.655     1709826.246      414619.169
     1710021.472      414533.231     1710296.646      414477.676
      1710528.33      414643.474     1710640.309      414767.606
      1710824.25      414839.655      1710990.37      415170.872

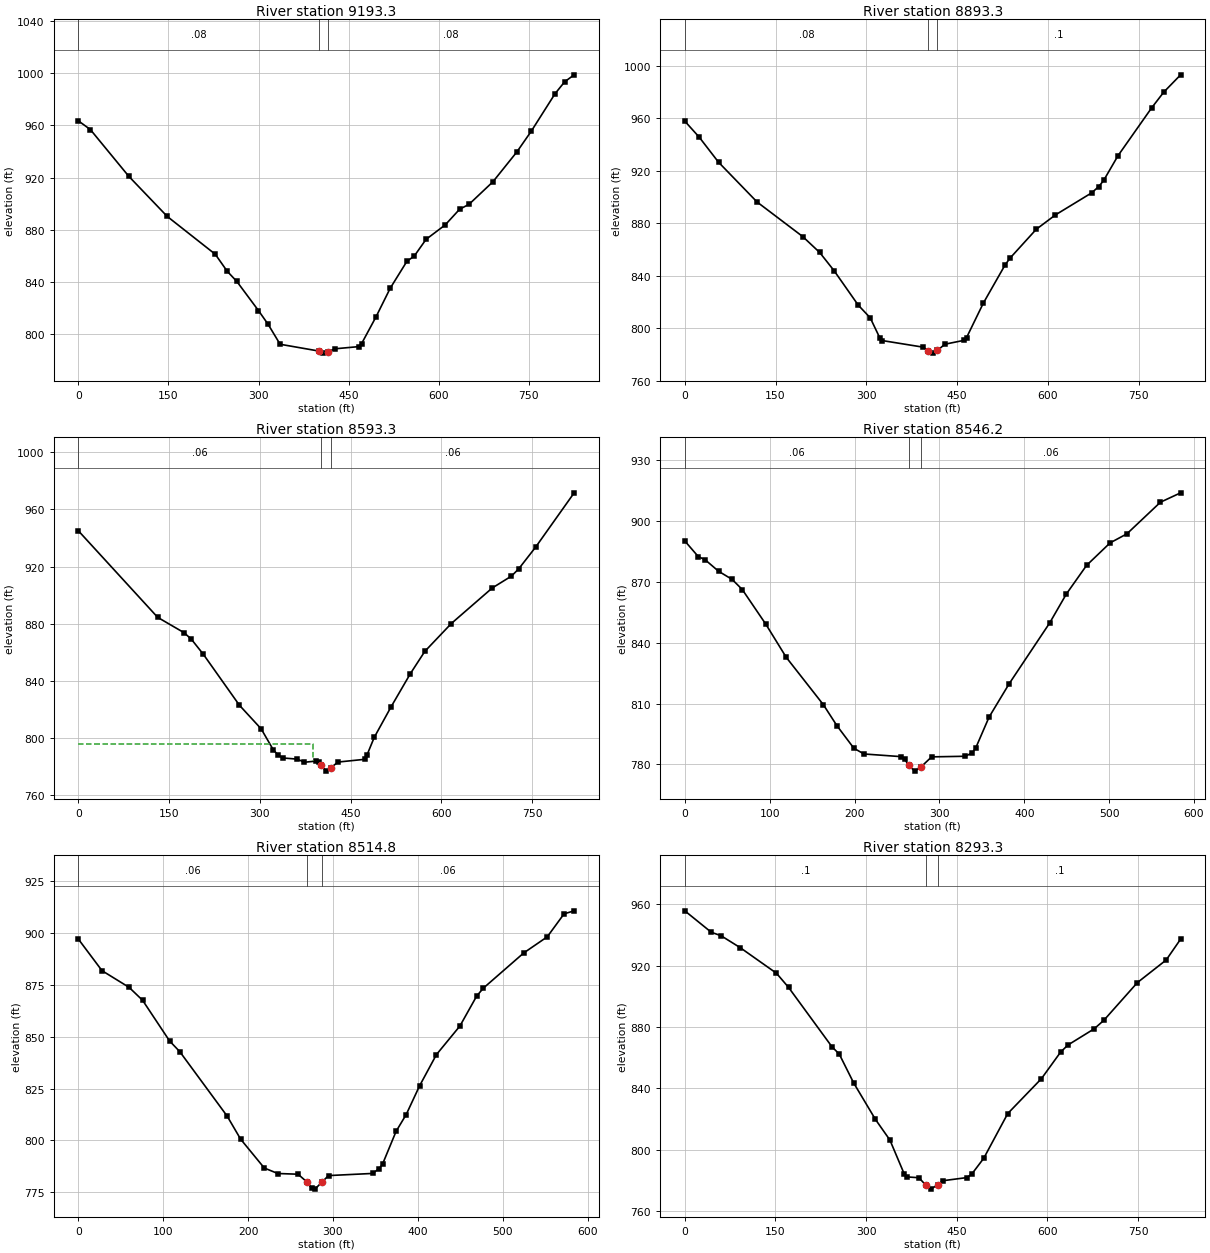
Type RM Length L Ch R = 1 ,9193.3  ,297.7,300,301
XS GIS Cut Line= 3
     1703786.777       414504.82     1704065.618      414207.105
     1704376.461      413928.319
#Sta/Elev= 30
       0  963.37      20   956.7      84  920.92     148  890.23     228  861.28
   247.9  848.26   263.9  840.47   299.9  818.21   315.9  807.72   335.9  792.45
   400.4  787.26   407.9  785.67   415.4  786.86   427.8  789.01   467.6  790.68
   471.5  792.91   495.4  813.29   519.2  835.31   547.1  855.99     559  859.79
   578.9  872.71   610.7  883.73   634.6  895.68   650.5  899.54   690.2  916.76
     730  939.56   753.9  955.35   793.6  984.12   809.6  993.24   825.4  998.55
#Mann= 3 , 0 , 0
       0     .08       0   400.4    .045       0   415.4     .08       0
Bank Sta=400.4,415.4
XS Rating Curve= 0 ,0
Exp/Cntr=0.3,0.1

Type RM Length L Ch R = 1 ,8893.3  ,300.7,300,297.8
XS GIS Cut Line= 3
     1703978.702      414680.307      1704285.74      414408.711
     1704603.501       414150.53
#Sta/Elev= 30
       0  957.77    23.9  945.52    55.7  926.49   119.4  896.16     195  869.75
   222.9  857.67   246.8  843.72   286.6  817.53   306.4  807.88   322.4  792.42
   326.4  790.51     394  785.48   402.4  782.47   409.9  780.94   417.4  782.95
   429.8  787.74   461.6   790.7   465.6  792.74   493.4  819.09   529.2  848.07
   537.1  853.16   580.8  875.33   612.6  886.32   672.3  903.09   684.2  907.94
   692.2  912.58     716  931.49   771.6  967.96   791.5  979.88   819.4  993.08
#Mann= 3 , 0 , 0
       0     .08       0   402.4    .045       0   417.4      .1       0
Bank Sta=402.4,417.4
XS Rating Curve= 0 ,0
Exp/Cntr=0.3,0.1

Type RM Length L Ch R = 1 ,8593.3  ,47.2,47.1,46.9
XS GIS Cut Line= 3
     1704197.603       414905.81     1704493.559      414622.721
     1704789.848      414339.159
#Sta/Elev= 30
       0  945.01   131.2  884.48     175  873.71   186.9  869.18   206.8  858.59
   266.4  823.01   302.2  806.59   322.1  792.06     330  788.33     338  786.22
   361.8   785.4   373.8  783.22   393.6  784.05   397.6  783.51     402  780.96
   409.6  777.01     417   779.3   429.5  783.36   473.3  785.26   477.2  788.25
   489.2   800.6     517  821.92   548.9  845.13   572.8   860.7   616.6  880.17
   684.3  905.02   716.1  913.34   728.1  918.42     756  933.56   819.7  971.52
#Mann= 3 , 0 , 0
       0     .06       0     402    .045       0     417     .06       0
#XS Ineff= 2 , 0
          388.29  796.11
Permanent Ineff=
       F       F
Bank Sta=402,417
XS Rating Curve= 0 ,0
Exp/Cntr=0.3,0.1

Type RM Length L Ch R = 1 ,8546.2  ,31.4,31.4,31.4
XS GIS Cut Line= 3
     1704333.185      414843.845     1704596.205      414588.636
     1704726.414      414414.157
#Sta/Elev= 30
       0  890.15    15.9  882.43    23.9   880.9    39.8  875.21    55.8  871.18
    67.7  866.21    95.6  849.02   119.5  832.78   163.3  809.39   179.3  799.03
   199.2  787.95   211.1  785.12     255   783.8   258.9   782.7   263.8   779.5
   270.9  776.66   278.8  778.93   290.8  783.69   330.6  783.99   338.6  785.68
   342.6   787.9   358.5   803.3   382.3  819.83   429.8  849.65   449.6  864.02
   473.4  878.11   501.1   889.2   520.9  893.66   560.4  909.25   584.2  913.88
#Mann= 3 , 0 , 0
       0     .06       0   263.8    .045       0   278.8     .06       0
Bank Sta=263.8,278.8
XS Rating Curve= 0 ,0
Exp/Cntr=0.3,0.1

Type RM Length L Ch R = 1 ,8514.8  ,224,221.5,217.5
XS GIS Cut Line= 3
     1704352.716      414868.584     1704615.737      414613.376
     1704745.945      414438.897
#Sta/Elev= 30
       0  897.05    27.9  881.81    59.8  873.77    75.7  867.54   107.6  847.88
   119.5  842.79   175.3  811.73   191.2   800.6   219.1  786.68     235  784.03
   258.9  783.69     269  780.07   274.9  777.03   278.8   776.5   286.8  779.81
   294.8  783.03   346.6  784.06   354.5  786.37   358.5  788.62   374.4  804.36
   386.3  812.45   402.1  826.32   421.9  841.34   449.6  855.14   469.4  869.61
   477.3  873.42   524.8  890.36   552.5  898.13   572.3   909.2   584.2  910.66
#Mann= 3 , 0 , 0
       0     .06       0     269    .045       0   286.8     .06       0
Bank Sta=269,286.8
XS Rating Curve= 0 ,0
Exp/Cntr=0.3,0.1

Type RM Length L Ch R = 1 ,8293.3  ,93.6,92.8,93
XS GIS Cut Line= 3
      1704465.43      415130.864      1704724.71      414811.572
     1704966.001      414481.147
#Sta/Elev= 30
       0  955.69    43.9  941.69    59.9  939.48    91.8  931.65   151.7  914.99
   171.7  905.76   243.6     867   255.6  862.27   279.5  843.42   315.5  819.65
   339.4  806.23   363.4  783.84   367.4  782.18   387.4  781.64   399.3  776.62
   407.3  774.21   418.8  777.14   427.2   779.7   466.9  781.74   474.9  784.03
   494.7  794.34   534.4  823.49   590.1  846.22   621.8  863.51   633.8  868.13
   677.4  878.74   693.3  884.23     749  908.91   796.6  923.63   820.5  937.24
#Mann= 3 , 0 , 0
       0      .1       0   399.3    .045       0   418.8      .1       0
Bank Sta=399.3,418.8
XS Rating Curve= 0 ,0
Exp/Cntr=0.3,0.1

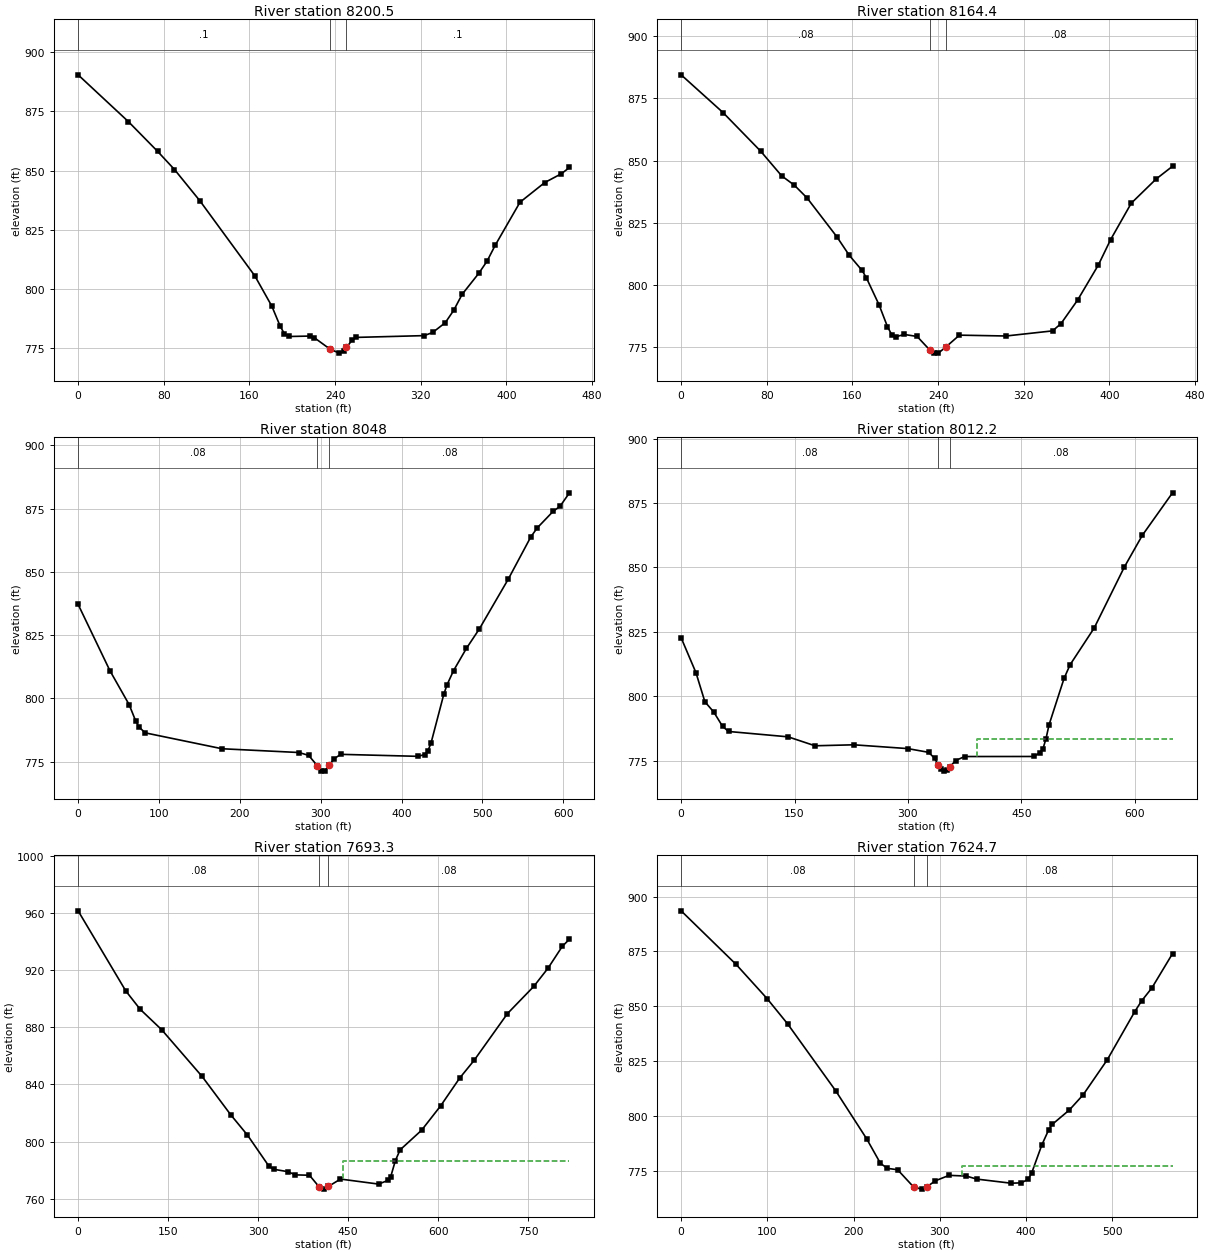
Type RM Length L Ch R = 1 ,8200.5  ,35.6,36.1,35.9
XS GIS Cut Line= 4
     1704607.924      414998.793     1704701.674      414993.584
      1704861.83      414782.647     1704877.455      414683.688
#Sta/Elev= 30
       0  890.47      47  870.67    74.3  858.09      90  850.45   113.7  837.24
     165  805.52   180.9  792.71   188.8  784.14   192.7  781.01   196.7  779.87
   216.4  780.05   220.4  779.42   235.6  774.42   244.1  772.84   248.1  773.58
   250.6  775.23     256  778.39   259.9  779.49   323.2  780.24   331.1  781.56
   342.9   785.7   350.8  790.95   358.7  797.73   374.2  806.57   381.9   811.7
   389.6  818.48   412.7  836.63   435.8  844.94   451.2  848.63   458.9   851.3
#Mann= 3 , 0 , 0
       0      .1       0   235.6    .045       0   250.6      .1       0
Bank Sta=235.6,250.6
XS Rating Curve= 0 ,0
Exp/Cntr=0.3,0.1

Type RM Length L Ch R = 1 ,8164.4  ,118.1,116.4,114.3
XS GIS Cut Line= 4
     1704631.362      415024.834     1704725.112      415019.626
     1704885.268      414808.688     1704900.893       414709.73
#Sta/Elev= 30
       0   884.5    39.1  869.33    74.3  853.78    93.9  843.86   105.8  840.08
   117.6  834.99   145.3  819.44   157.1  811.86     169  805.82     173  802.86
   184.8  792.04   192.7   783.2   196.7  779.96   200.6  779.18   208.5  780.07
   220.4  779.27   232.2  773.83   236.2  772.69   240.2  772.57   247.2  775.02
   259.9   779.8   303.4  779.46   346.9  781.52   354.8  784.46   370.3  793.93
   389.6  807.98   401.1  818.22   420.4  832.88   443.5  842.56   458.9  847.72
#Mann= 3 , 0 , 0
       0     .08       0   232.2    .045       0   247.2     .08       0
Bank Sta=232.2,247.2
XS Rating Curve= 0 ,0
Exp/Cntr=0.3,0.1

Type RM Length L Ch R = 1 ,8048    ,36.1,35.8,35.9
XS GIS Cut Line= 4
     1704715.997       415091.24     1704796.726       415140.72
      1704911.31       414959.73     1705068.862      414705.824
#Sta/Elev= 30
       0  837.14    39.4  810.92    63.1  797.55      71  791.26      75  788.84
    82.8  786.41     178  780.12   273.2  778.63   285.1   777.5   295.8  773.44
     301  771.46   304.9  771.28   310.8  773.75   316.9  776.23   324.8  777.91
   420.5  777.12   428.4  777.83   432.4  779.16   436.4  782.29   452.3  801.68
   456.3   805.4   464.3  810.96   480.2  819.74   496.2  827.43     532  847.11
   559.9  863.81   567.9  867.37   587.8  873.99   595.8   875.8   607.7   881.2
#Mann= 3 , 0 , 0
       0     .08       0   295.8    .045       0   310.8     .08       0
Bank Sta=295.8,310.8
XS Rating Curve= 0 ,0
Exp/Cntr=0.3,0.1

Type RM Length L Ch R = 1 ,8012.2  ,328.7,318.8,308.6
XS GIS Cut Line= 4
     1704721.205      415127.699     1704811.049      415183.688
      1704942.56      414976.657     1705100.112      414722.751
#Sta/Elev= 30
       0  822.73    19.6   809.2    31.4  797.94    43.1  793.95    54.9  788.35
    62.7   786.4   141.5  784.32   177.1  780.85   228.5  781.23   299.7  779.76
   327.4  778.31   335.3     776   340.4  773.21   343.2  771.66   347.2  771.02
   351.1  771.28   355.4  772.69   363.1  775.12     375  776.68   466.7   776.7
   474.6  778.17   478.6  779.68   482.6  783.52   486.6   788.9   506.5  806.95
   514.5  812.27   546.4  826.53   586.2  850.12   610.1  862.49     650  878.95
#Mann= 3 , 0 , 0
       0     .08       0   340.4    .045       0   355.4     .08       0
#XS Ineff= 2 , 0
                          391.35          783.57
Permanent Ineff=
       F       F
Bank Sta=340.4,355.4
XS Rating Curve= 0 ,0
Exp/Cntr=0.3,0.1

Type RM Length L Ch R = 1 ,7693.3  ,70.3,68.7,67.1
XS GIS Cut Line= 3
     1705198.201      415391.761     1705248.991      414985.423
     1705299.781      414579.085
#Sta/Elev= 30
       0   961.5    79.5  905.43   103.4  892.63   139.2  878.35   206.7   845.6
   254.4  818.79   282.3  804.57   318.1   782.8     326  780.66   349.9  778.98
   361.8  776.76   385.6  776.49     402  768.21   409.5  766.78     417  768.62
   437.3  773.82   500.9  770.31   516.8  772.96   520.8  775.13   528.8  786.73
   536.7  794.26   572.5  807.99   604.3  825.07   636.1  844.54     660  856.85
   715.6  889.59   759.4  908.58   783.2  921.34   807.1  936.69     819  941.66
#Mann= 3 , 0 , 0
       0     .08       0     402    .045       0     417     .08       0
#XS Ineff= 2 , 0
                          441.49          786.56
Permanent Ineff=
       F       F
Bank Sta=402,417
XS Rating Curve= 0 ,0
Exp/Cntr=0.3,0.1

Type RM Length L Ch R = 1 ,7624.7  ,20.9,20.9,20.9
XS GIS Cut Line= 2
     1705301.935      415270.928     1705333.185      414701.918
#Sta/Elev= 30
       0  893.49    63.8  869.05    99.6  853.54   123.5  841.99   179.3  811.48
   215.2  789.61   231.1  778.49   239.1  776.17   251.1  775.53   269.9  767.55
     279   766.7   284.9  767.73   294.9  770.51   310.8  772.98   330.8  772.65
   342.7  771.28   382.6   769.4   394.5  769.56   402.5  771.19   406.5     774
   418.4  786.89   426.4  793.81   430.4  796.19   450.3  802.77   466.3  809.69
   494.2  825.61     526  847.49     534  852.42     546  858.37   569.9  873.98
#Mann= 3 , 0 , 0
       0     .08       0   269.9    .045       0   284.9     .08       0
#XS Ineff= 2 , 0
                          325.61          777.33
Permanent Ineff=
       F       F
Bank Sta=269.9,284.9
XS Rating Curve= 0 ,0
Exp/Cntr=0.3,0.1

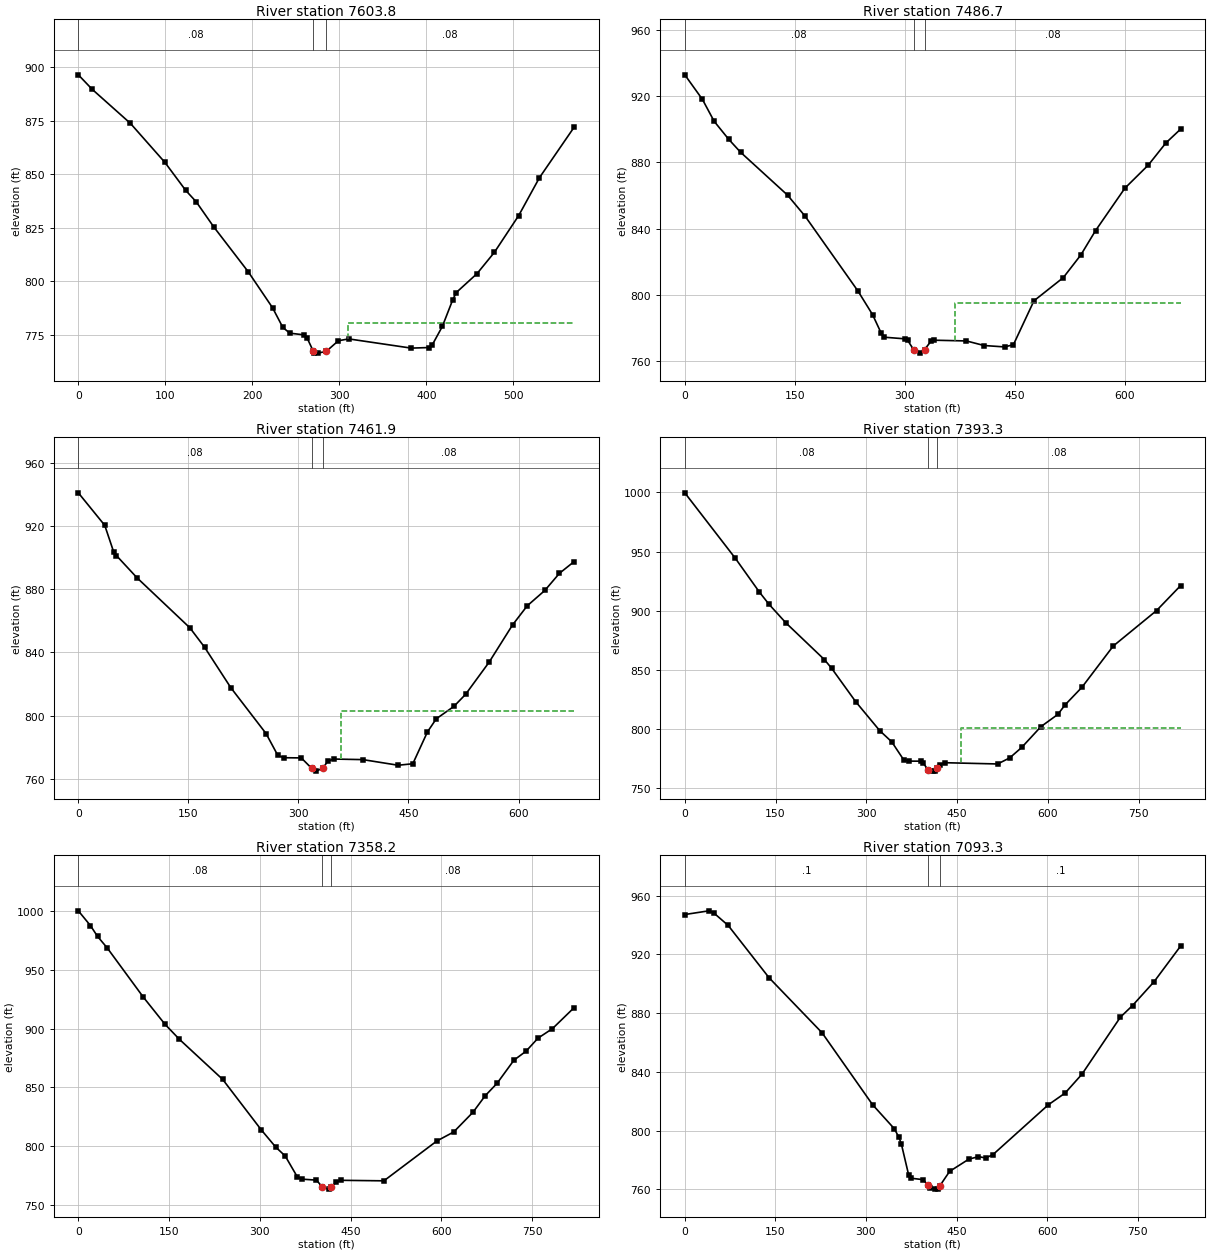
Type RM Length L Ch R = 1 ,7603.8  ,118.3,117,115.4
XS GIS Cut Line= 2
     1705322.768       415272.23     1705354.018       414703.22
#Sta/Elev= 30
       0   896.4    15.9  889.65    59.8  873.77    99.6  855.48   123.5  842.42
   135.5  837.13   155.4  825.56   195.3  804.46   223.2   787.7   235.1  778.47
   243.1  775.82     259  775.04     263  773.52   269.9  767.54     271  766.71
     275   766.5   284.9   767.3   298.9  772.28   310.8  773.14   382.6  768.84
   402.5   769.1   406.5  770.12   418.4  778.96   430.4  791.46   434.4  794.78
   458.3  803.63   478.2  813.54   506.1  830.68     530  848.39   569.9  871.98
#Mann= 3 , 0 , 0
       0     .08       0   269.9    .045       0   284.9     .08       0
#XS Ineff= 2 , 0
                          310.34           780.5
Permanent Ineff=
       F       F
Bank Sta=269.9,284.9
XS Rating Curve= 0 ,0
Exp/Cntr=0.3,0.1

Type RM Length L Ch R = 1 ,7486.7  ,24.8,24.8,24.7
XS GIS Cut Line= 2
     1705456.883       415309.99     1705450.372      414634.209
#Sta/Elev= 30
       0  932.87      24  918.04      40   904.8      60  893.83      76   886.1
     140  860.19     164  847.43   235.9   802.3   255.9  787.98   267.9  776.57
   271.9  774.32   299.9  773.34   303.9  772.34   311.8  766.83   319.9   764.7
   326.8  766.82   335.9  772.13   339.9  772.51   383.9  772.06   407.9   769.3
   435.9  768.45   447.9  769.79   475.9  796.32   515.9  810.34   539.8  824.02
   559.8  838.71   599.8  864.35   631.8  878.37   655.8  891.75   675.8  900.07
#Mann= 3 , 0 , 0
       0     .08       0   311.8    .045       0   326.8     .08       0
#XS Ineff= 2 , 0
                           368.8          795.14
Permanent Ineff=
       F       F
Bank Sta=311.8,326.8
XS Rating Curve= 0 ,0
Exp/Cntr=0.3,0.1

Type RM Length L Ch R = 1 ,7461.9  ,68.3,68.6,68.5
XS GIS Cut Line= 2
     1705481.622      415315.199     1705475.112      414639.418
#Sta/Elev= 30
       0  940.93      36  920.37      48  903.77      52   901.2      80  887.19
     152  855.57     172  843.32   207.9  817.64   255.9  788.65   271.9  774.85
   279.9  773.39   303.9  773.27   318.2   766.6   323.9  764.91   333.2  766.71
   339.9  771.13   347.9  772.55   387.9  772.19   435.9  768.63   455.9  769.58
   475.9  789.77   487.9  798.02   511.9  805.85   527.8  813.46   559.8  833.76
   591.8  857.36   611.8  869.45   635.8  879.18   655.8  890.05   675.8  897.46
#Mann= 3 , 0 , 0
       0     .08       0   318.2    .045       0   333.2     .08       0
#XS Ineff= 2 , 0
                          358.51           803.1
Permanent Ineff=
       F       F
Bank Sta=318.2,333.2
XS Rating Curve= 0 ,0
Exp/Cntr=0.3,0.1

Type RM Length L Ch R = 1 ,7393.3  ,35.3,35.2,35.3
XS GIS Cut Line= 3
     1705546.999      415401.523     1705546.999      414992.085
     1705543.036      414582.251
#Sta/Elev= 30
       0   999.7    83.5   944.3   123.2  915.74   139.1   905.4     167  889.67
   230.6  858.58   242.5  851.29   282.2  823.07     322  798.48   341.9  788.99
   361.7  773.74   369.7  772.65   389.6  772.59   393.5   771.4   401.9  765.22
   409.4  764.17   413.4  764.62   416.9  766.49   421.4  769.34   429.3   771.3
   516.9  770.23   536.8  775.34   556.7  784.21   588.5  801.84   616.4  812.17
   628.3   820.2   656.2  835.12   707.9  870.02   779.5  900.05   819.3  921.19
#Mann= 3 , 0 , 0
       0     .08       0   401.9    .045       0   416.9     .08       0
#XS Ineff= 2 , 0
                          456.19           800.3
Permanent Ineff=
       F       F
Bank Sta=401.9,416.9
XS Rating Curve= 0 ,0
Exp/Cntr=0.3,0.1

Type RM Length L Ch R = 1 ,7358.2  ,269.2,264.8,259
XS GIS Cut Line= 3
     1705582.155      415401.523     1705582.155      414992.085
     1705578.192      414582.251
#Sta/Elev= 30
       0  1000.1    19.9  987.63    31.8  978.33    47.7   968.6   107.3  926.82
   143.1  903.76     167  890.92   238.5  856.86   302.1   814.1     326  799.42
   341.9  791.73   361.7  774.16   369.7   772.1   393.5  771.26   403.1  765.46
   413.4  763.62   418.1  765.02   425.4  769.33   433.3  771.12   504.9  770.67
   592.5  804.56   620.3  812.19   652.2  828.99   672.1  842.85     692  853.59
   719.8  873.21   739.7  880.78   759.6  891.91   783.5  900.02   819.3  917.87
#Mann= 3 , 0 , 0
       0     .08       0   403.1    .045       0   418.1     .08       0
Bank Sta=403.1,418.1
XS Rating Curve= 0 ,0
Exp/Cntr=0.3,0.1

Type RM Length L Ch R = 1 ,7093.3  ,32,31.8,31.7
XS GIS Cut Line= 3
     1705924.588       415346.53     1705841.542      414944.341
     1705736.709      414547.456
#Sta/Elev= 30
       0  947.09    39.9  949.61    47.8  948.24    71.8  939.69   139.6  904.06
   227.3  866.65     311   817.7   346.9  801.39   354.8  795.44   358.8  790.74
   370.8  769.81   374.8  767.66   394.7   766.7   403.2  762.83   406.7  761.24
   414.7  760.25   418.6  760.54   422.6  762.62   438.6  772.32   470.4  780.64
   486.4  782.34   498.4  781.46   510.3   783.7     602   817.6   629.9  825.63
   657.8  838.45   721.5  877.29   741.5  885.15   777.3  901.42   821.2  925.65
#Mann= 3 , 0 , 0
       0      .1       0   403.2    .045       0   422.6      .1       0
Bank Sta=403.2,422.6
XS Rating Curve= 0 ,0
Exp/Cntr=0.3,0.1

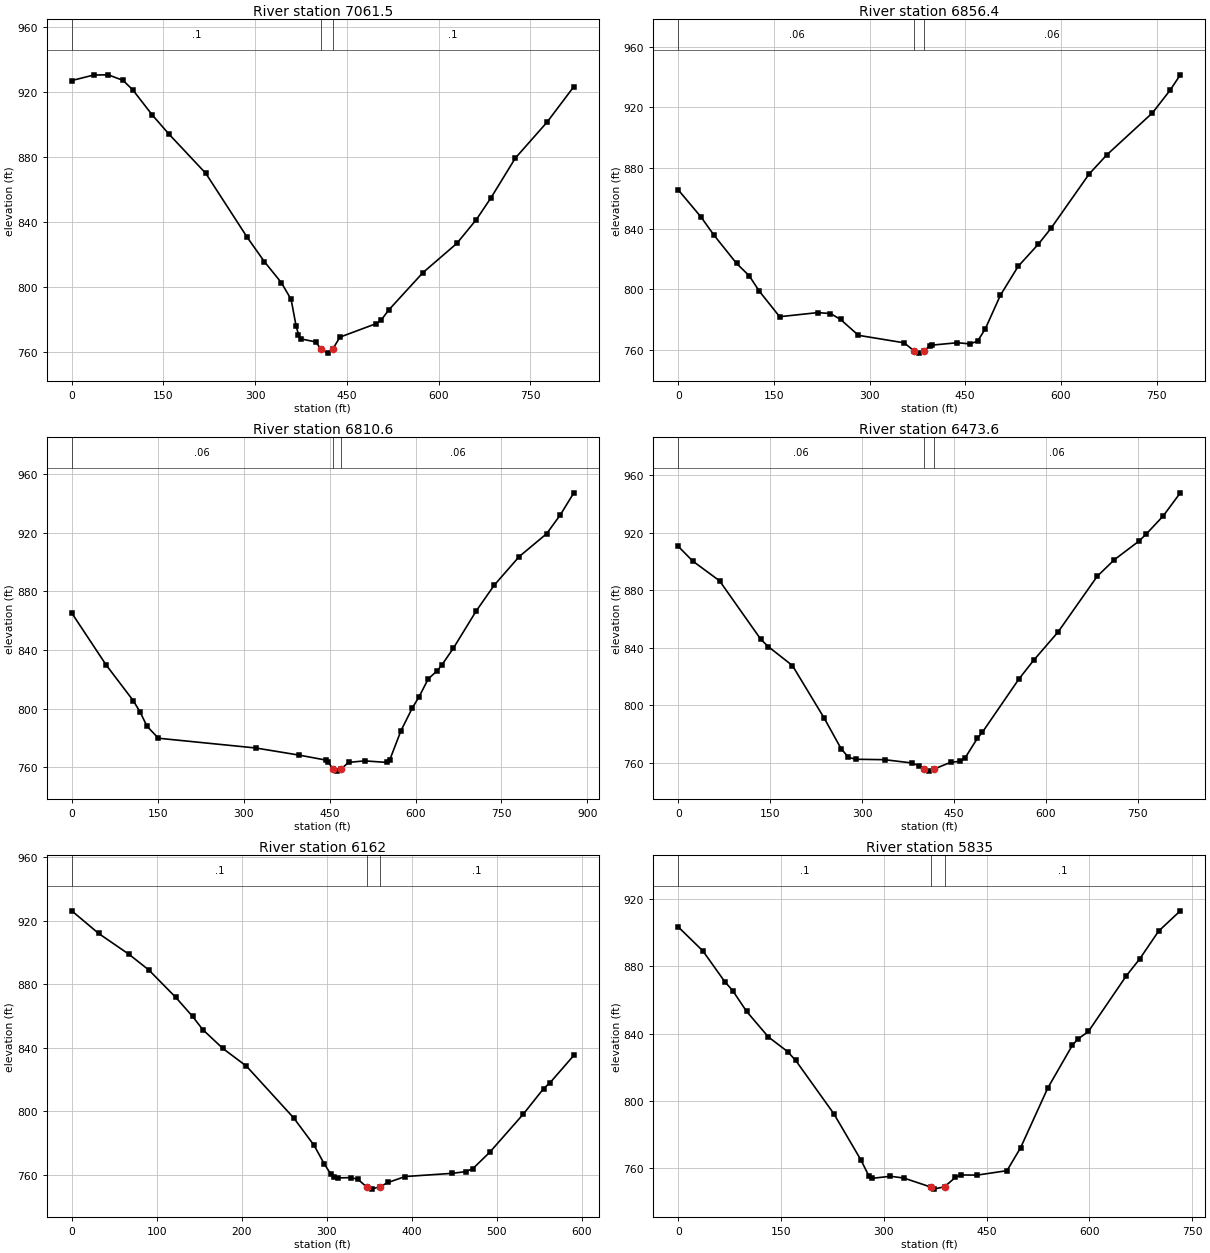
Type RM Length L Ch R = 1 ,7061.5  ,210.1,205.1,200.8
XS GIS Cut Line= 3
     1705955.838      415342.624     1705872.792      414940.435
     1705767.959       414543.55
#Sta/Elev= 30
       0  927.21    35.9   930.6    59.8  930.72    83.7  927.32    99.7  921.53
   131.6  906.04   159.5  894.04   219.3  870.09   287.1   830.7     315  815.83
   342.9  802.86   358.8  792.55   366.8  776.47   370.8  770.99   374.8  768.32
   398.7  766.46   408.4  761.84   418.6  759.56   426.6  761.87   438.6  769.39
   498.4  777.77   506.3  779.99   518.3  786.03   574.1  808.97   629.9  827.08
   661.8  841.73   685.7  855.11   725.5   879.5   777.3  901.57   821.2  923.46
#Mann= 3 , 0 , 0
       0      .1       0   408.4    .045       0   426.6      .1       0
Bank Sta=408.4,426.6
XS Rating Curve= 0 ,0
Exp/Cntr=0.3,0.1

Type RM Length L Ch R = 1 ,6856.4  ,45.9,45.9,45.9
XS GIS Cut Line= 4
     1706016.778      415138.115     1706160.008      415069.105
     1706063.594      414867.887     1705893.564      414500.211
#Sta/Elev= 30
       0  865.55    35.8  847.59    55.6   835.9    91.4  817.04   111.3  808.85
   127.2  798.64     159  781.86   218.8  784.56   238.7  783.96   254.6  780.02
   282.5  769.58   354.2  764.63   370.4  759.08   378.1  757.83   385.4  759.18
     394  762.63     398  763.11   437.7   764.7   457.6   763.9   469.5  765.82
   481.4  773.81   505.2  796.09     533   815.1   564.8   829.8   584.7  840.33
   644.2  875.98     672  888.65   743.5  916.33   771.3  931.34   787.2  941.44
#Mann= 3 , 0 , 0
       0     .06       0   370.4    .045       0   385.4     .06       0
Bank Sta=370.4,385.4
XS Rating Curve= 0 ,0
Exp/Cntr=0.3,0.1

Type RM Length L Ch R = 1 ,6810.6  ,348.4,337,325
XS GIS Cut Line= 4
     1706038.378      415180.453     1706220.948      415091.879
      1706105.26      414849.658     1705935.231      414481.982
#Sta/Elev= 30
       0  865.24    59.7     830   107.4  805.46   119.4  797.64   131.3  788.08
   151.2  779.88   321.4  773.22   396.4   768.4   443.7  764.97   447.7  763.78
   455.2  759.08   463.5  757.45   470.2  758.99   483.3   763.4   511.1  764.44
   550.8  763.37   554.8  764.84   574.6  784.98   594.5  800.58   606.4  808.23
   622.3   820.4   638.2  825.96   646.1  829.92     666  841.19   705.7   866.5
   737.4  884.22   781.1  903.77   828.8  919.28   852.6  932.06   876.4  947.21
#Mann= 3 , 0 , 0
       0     .06       0   455.2    .045       0   470.2     .06       0
Bank Sta=455.2,470.2
XS Rating Curve= 0 ,0
Exp/Cntr=0.3,0.1

Type RM Length L Ch R = 1 ,6473.6  ,319.8,311.6,300.7
XS GIS Cut Line= 3
     1706690.479      414871.028     1706356.443      414635.853
     1706019.793      414400.123
#Sta/Elev= 30
       0  910.44    23.8  900.18    67.4  886.54   134.8  845.89   146.8  840.89
   186.4  827.68     238  791.36   265.7  770.08   277.6  764.05   289.5  762.64
   337.1  762.32   380.8  760.08   392.6  758.24   400.6  755.53   408.5  754.39
   417.2  755.76   444.4  760.47   460.4  761.25   468.4  763.69   488.3  777.17
   496.3   781.3   556.2  818.42   580.1  831.34     620     851   683.8  889.62
   711.8  901.15   751.7  913.98   763.6  918.85   791.6  931.56   819.5  947.61
#Mann= 3 , 0 , 0
       0     .06       0   400.6    .045       0   417.2     .06       0
Bank Sta=400.6,417.2
XS Rating Curve= 0 ,0
Exp/Cntr=0.3,0.1

Type RM Length L Ch R = 1 ,6162    ,322.3,327,332.5
XS GIS Cut Line= 4
     1706822.809       414485.82     1706663.704      414406.427
     1706493.822       414364.71     1706258.832       414326.75
#Sta/Elev= 30
       0  926.33    31.6  912.09    67.2  899.01    90.9  888.98   122.5  871.77
   142.2  859.83   154.1  851.57   177.8  839.68   205.6  828.52   261.3  795.86
   285.2  778.64   297.1  766.98     305  760.44     309   758.6     313  758.18
   328.9  758.37   336.8  757.26   347.7  752.16   352.7  751.12   362.7  752.68
   372.6   755.4   392.4  759.05     448  761.08   463.8  762.16   471.8  763.93
   491.6   774.2   531.3  798.32   555.1  814.34     563  818.24   590.8  835.34
#Mann= 3 , 0 , 0
       0      .1       0   347.7    .045       0   362.7      .1       0
Bank Sta=347.7,362.7
XS Rating Curve= 0 ,0
Exp/Cntr=0.3,0.1

Type RM Length L Ch R = 1 ,5835    ,300.7,297.4,293.3
XS GIS Cut Line= 5
     1706920.421      414261.675     1706765.196      414136.412
      1706602.28      414066.452     1706421.425       413984.92
      1706267.87      413948.957
#Sta/Elev= 30
       0  903.46    35.9  889.23    67.8  871.01    79.8  865.44    99.7  853.31
   131.6  838.07   159.6   829.4   171.5  824.11     227  792.54   266.4  765.18
   278.3  755.51   282.2  754.04   309.8  755.32   329.5  754.24   369.1  748.84
   372.8  747.67   388.7  749.07   404.5  754.64   412.5  756.08   436.3     756
   479.9  758.64   499.8  772.29   539.4  807.71   575.2  833.06     583  836.69
   598.8  841.36     654  874.36   673.7  884.48   701.3  900.99   732.9  913.02
#Mann= 3 , 0 , 0
       0      .1       0   369.1    .045       0   388.7      .1       0
Bank Sta=369.1,388.7
XS Rating Curve= 0 ,0
Exp/Cntr=0.3,0.1

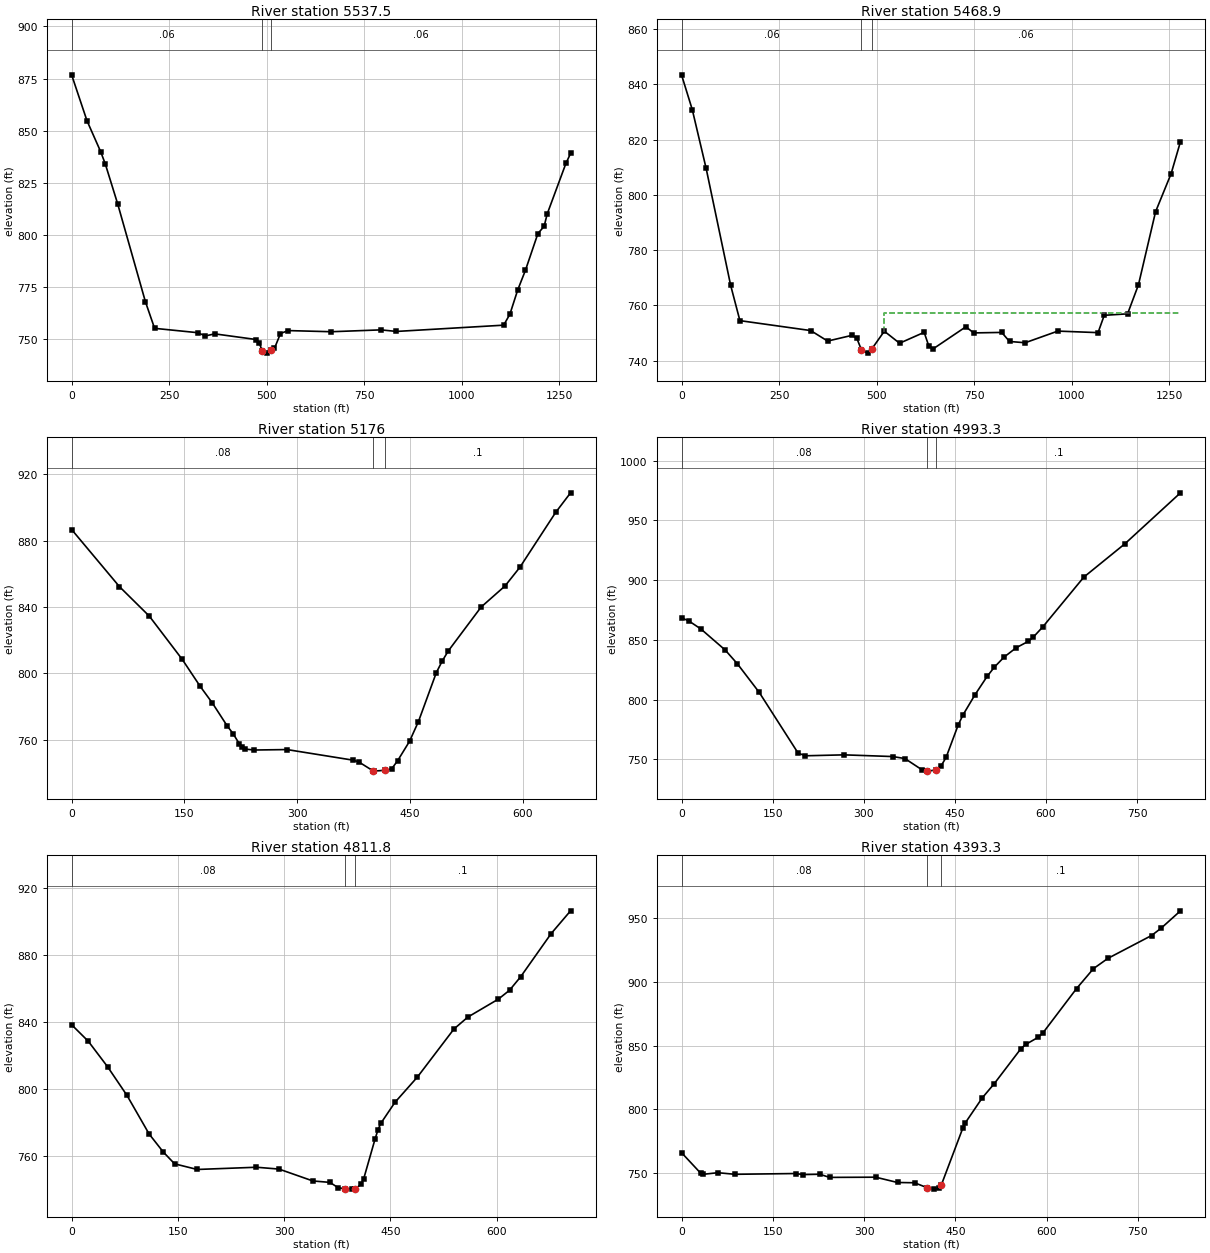
Type RM Length L Ch R = 1 ,5537.5  ,68.6,68.7,69
XS GIS Cut Line= 6
     1707093.953      414158.641     1707072.261      413947.149
     1706721.583      413858.576     1706593.242      413797.117
      1706381.75      413518.743     1706188.334      413603.701
#Sta/Elev= 30
       0  876.78    39.4  854.74    74.8  839.74    86.6  833.83   118.1   814.8
     189  767.94   212.6  755.12   323.1  753.03   342.8  751.47   366.5  752.47
   472.8  749.75   480.6  748.21   488.4  744.21   500.1  743.22   511.8  744.58
   519.6  745.45   535.2  752.63   554.8  754.04   665.2  753.49   792.5  754.38
   832.4  753.63    1107  756.64    1123  761.92  1142.9  773.49  1162.8  782.99
  1194.7   800.6  1210.6  804.06  1218.6  810.05  1266.4  834.23  1278.4  839.06
#Mann= 3 , 0 , 0
       0     .06       0   488.4    .045       0   511.8     .06       0
Bank Sta=488.4,511.8
XS Rating Curve= 0 ,0
Exp/Cntr=0.3,0.1

Type RM Length L Ch R = 1 ,5468.9  ,264.4,292.9,320.5
XS GIS Cut Line= 6
     1707108.414      414093.567     1707086.722      413882.075
     1706736.044      413793.501     1706607.702      413732.042
     1706396.211      413453.669     1706202.795      413538.627
#Sta/Elev= 30
       0  843.42    27.6  830.81      63  809.63     126  767.23   149.6  754.52
     331  750.93   374.4  747.13   437.5  749.23   449.3  748.09   461.1   743.9
   476.7  742.77   486.8  744.13   519.6   750.7   558.7  746.35   621.7  750.29
   633.6  745.32   645.4  744.38   728.6   752.3   748.5  750.08   820.4  750.26
   840.4  746.99   880.4  746.52   964.2  750.74  1067.2  750.18  1083.1  756.45
  1142.9  756.98  1170.8  767.51  1214.6   793.9  1254.5   807.7  1278.4  819.26
#Mann= 3 , 0 , 0
       0     .06       0   461.1    .045       0   486.8     .06       0
#XS Ineff= 2 , 0
                          517.58          757.43
Permanent Ineff=
       F       F
Bank Sta=461.1,486.8
XS Rating Curve= 0 ,0
Exp/Cntr=0.3,0.1

Type RM Length L Ch R = 1 ,5176    ,180.8,182.7,183.1
XS GIS Cut Line= 3
     1707133.523       414175.53      1707088.53      413748.311
     1707068.646      413515.128
#Sta/Elev= 30
       0  886.63    63.6   852.2   103.4  834.38   147.2  808.29     171  792.09
     187  782.17   206.8  768.32   214.8  763.55   222.8  757.63   226.7  755.67
   230.7  754.29   242.6   753.7   286.4  753.98   373.9  747.62   381.8  746.56
   401.3  741.04   401.7  740.98   416.3  741.48   425.6  742.32   433.6  747.26
   449.4  758.93   461.3  770.88   485.1   800.4     493  807.42     501  813.46
   544.6  839.87   576.4  852.58   596.2  863.86   643.8  896.95   663.6  908.74
#Mann= 3 , 0 , 0
       0     .08       0   401.3    .045       0   416.3      .1       0
Bank Sta=401.3,416.3
XS Rating Curve= 0 ,0
Exp/Cntr=0.3,0.1

Type RM Length L Ch R = 1 ,4993.3  ,178.7,181.5,185
XS GIS Cut Line= 3
     1707280.345       414175.12     1707272.857      413763.419
     1707236.532      413355.281
#Sta/Elev= 30
       0  868.44      12  865.83      32  859.05      72  841.43      92  829.93
   127.9  806.05   191.9  755.25   203.9  752.96   267.8  753.74   347.8  752.32
   367.8  750.64   395.8  741.27   403.8  740.12   404.3  740.13   419.3  741.06
   427.7  744.79   435.6  751.57   455.5  778.69   463.5  787.24   483.4  804.19
   503.3  819.49   515.2  827.21   531.1  835.56     551  843.37   570.9  848.71
   578.8  852.06   594.8  860.82   662.4   902.5     730  930.39   821.5  973.04
#Mann= 3 , 0 , 0
       0     .08       0   404.3    .045       0   419.3      .1       0
Bank Sta=404.3,419.3
XS Rating Curve= 0 ,0
Exp/Cntr=0.3,0.1

Type RM Length L Ch R = 1 ,4811.8  ,412.9,418.5,423.2
XS GIS Cut Line= 5
     1707332.559      414118.873     1707423.237      414057.445
     1707452.943      413772.071       1707460.9      413652.507
     1707363.288      413491.629
#Sta/Elev= 30
       0  838.46    23.5  828.62    50.8  813.36    78.2  796.24   109.5  773.16
   129.4  762.46   145.4  755.39   177.3  752.03     261  753.36   292.8  752.26
   340.6  745.17   364.6  744.32   376.5   741.1   385.4  740.57   396.4  740.29
   400.4  740.43   408.4  743.11   412.4  746.55   428.4  770.22   432.4  775.57
   436.4  779.49   456.4  792.07   488.3  807.29   539.8  835.93   559.4  843.04
   602.5  853.77   618.2  859.04   633.9  867.09     677   892.9   704.4  906.49
#Mann= 3 , 0 , 0
       0     .08       0   385.4    .045       0   400.4      .1       0
Bank Sta=385.4,400.4
XS Rating Curve= 0 ,0
Exp/Cntr=0.3,0.1

Type RM Length L Ch R = 1 ,4393.3  ,297.4,300,302.8
XS GIS Cut Line= 3
       1707724.7      414248.772      1707858.76      413860.368
     1707980.065      413469.504
#Sta/Elev= 30
       0  765.87    31.9  749.52    35.9  748.87    59.8  750.12    87.8  748.86
   187.5  749.47   199.5  748.64   227.4   748.9   243.3  746.43   319.1   746.6
     355  742.43     383  742.22   403.4  738.39   414.9  737.22   422.8  737.77
   426.8  740.18   462.5  785.33   466.5  789.29   494.3  808.87   514.2  820.13
   557.9  847.55   565.8  850.86   585.7  856.29   593.7  859.68   649.3  894.71
   677.1  910.36   700.9  918.43   772.5  936.34   788.4  942.15   820.1  955.75
#Mann= 3 , 0 , 0
       0     .08       0   403.4    .045       0   426.8      .1       0
Bank Sta=403.4,426.8
XS Rating Curve= 0 ,0
Exp/Cntr=0.3,0.1