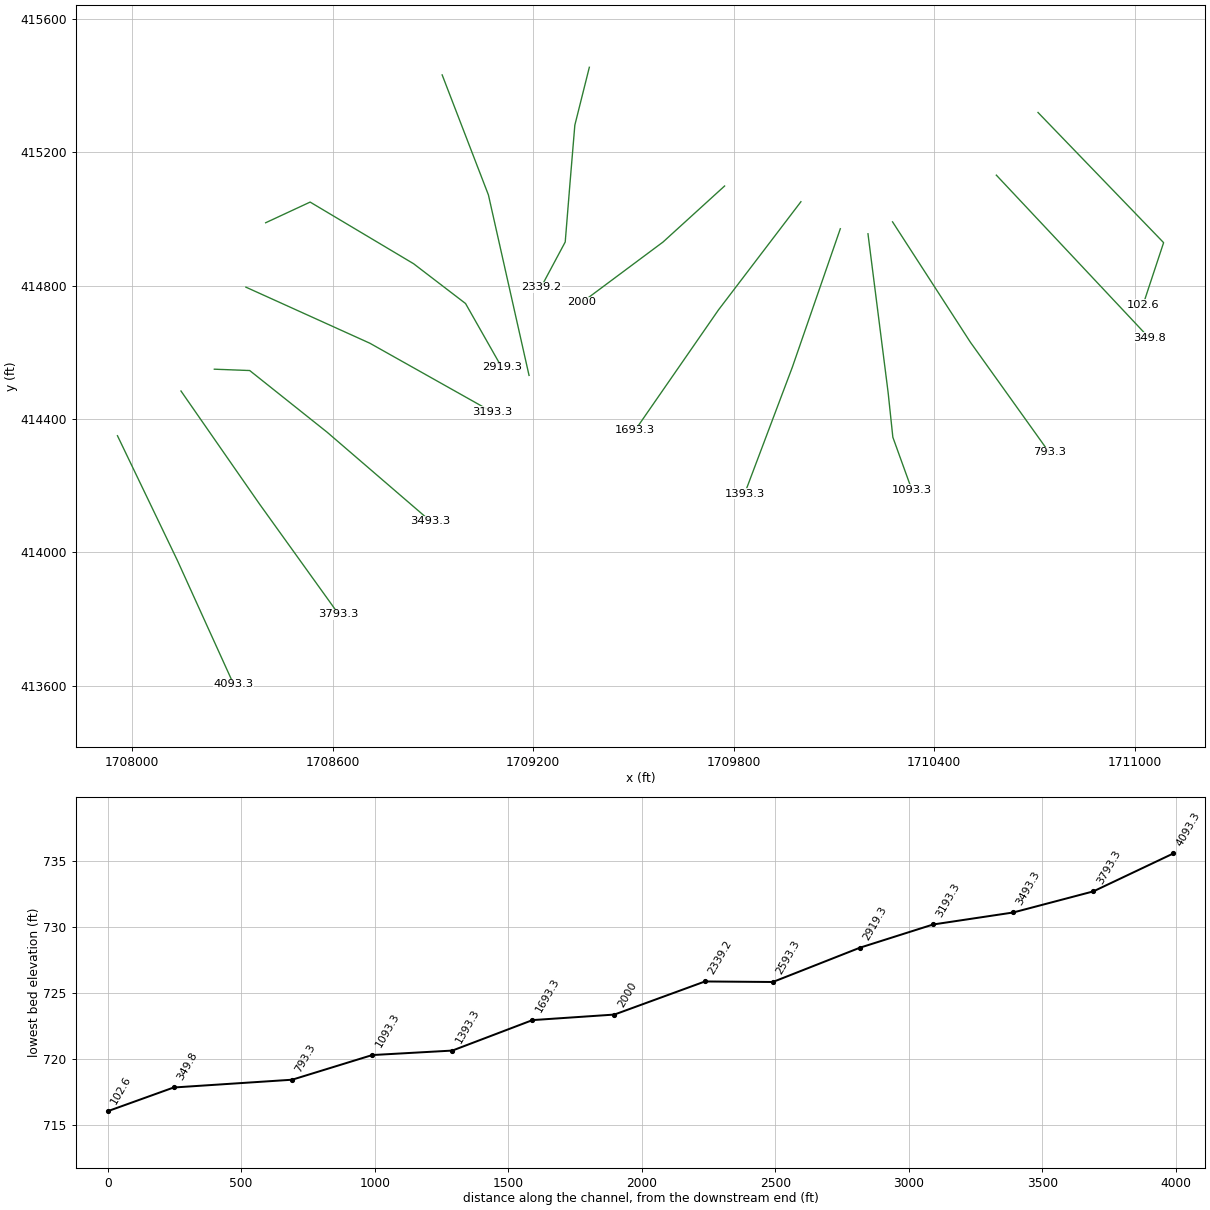
HEC-RAS study DODSONFK.prj: DODSONFK

--- DODSONFK.g01 (geometry) --- (continued)

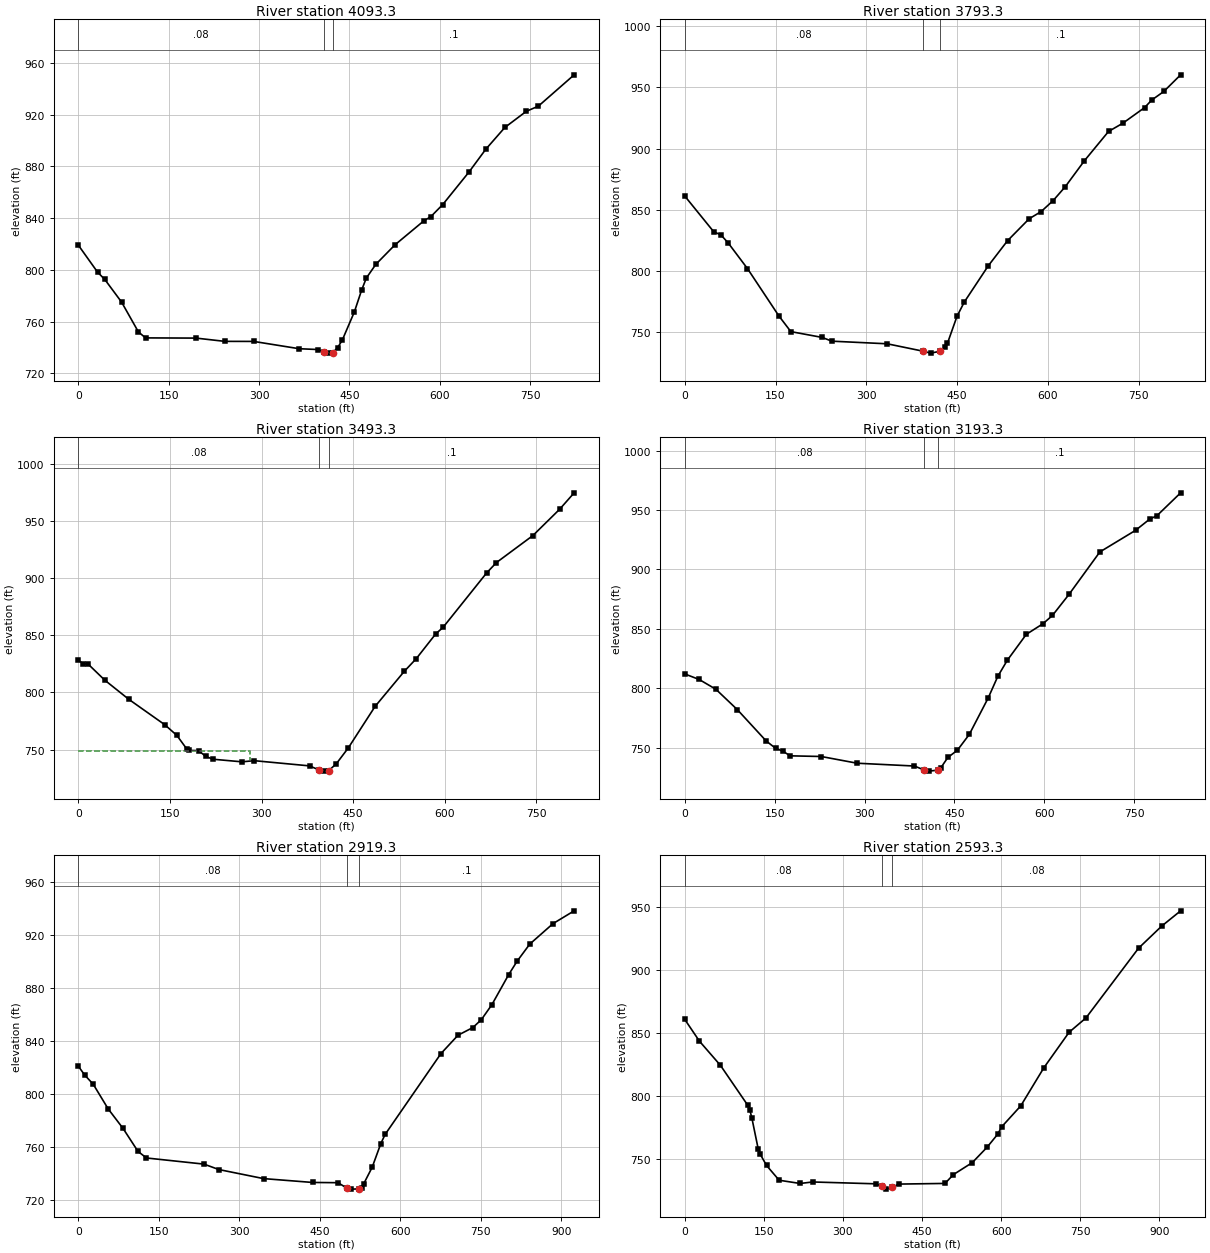
Type RM Length L Ch R = 1 ,4093.3  ,296.4,300,304.4
XS GIS Cut Line= 3
     1707955.472      414349.476     1708134.737      413975.584
     1708303.332      413603.486
#Sta/Elev= 30
       0  819.12    31.9  798.27    43.9  792.61    71.8  775.08    99.7  752.03
   111.6  747.38   195.4  747.23   243.2   744.7     291  744.66   366.8     739
   398.7  738.37   407.1  736.47   414.6   735.6   422.1  735.95   430.5  739.78
   438.4  745.87   458.3  767.51   470.2  784.18   478.1  793.64     494  804.32
   525.7  819.36   573.3  837.79   585.2  841.16     605  850.52   648.6   875.7
   676.4  893.27   708.1  910.14   743.8  922.67   763.7  926.62   823.2  950.88
#Mann= 3 , 0 , 0
       0     .08       0   407.1    .045       0   422.1      .1       0
Bank Sta=407.1,422.1
XS Rating Curve= 0 ,0
Exp/Cntr=0.3,0.1

Type RM Length L Ch R = 1 ,3793.3  ,293.4,300,305
XS GIS Cut Line= 3
       1708145.6      414483.605     1708379.386      414146.403
     1708617.782      413813.722
#Sta/Elev= 30
       0  861.15    47.8  831.98    59.8  829.37    71.7  822.84   103.6  801.85
   155.4  763.22   175.3  750.31   227.1  745.56     243   742.5   334.6  740.35
   394.4  734.25   406.3  732.72   422.2  734.26   430.2  737.36   434.2  740.79
     450  762.88     462  774.49   501.7  804.17   533.5  824.66   569.3  842.63
   589.1   848.5     609  857.53   628.9   868.8   660.6  890.08   700.4  913.98
   724.2  920.78     760   933.5   771.9   939.7   791.8   946.7   819.6  960.31
#Mann= 3 , 0 , 0
       0     .08       0   394.4    .045       0   422.2      .1       0
Bank Sta=394.4,422.2
XS Rating Curve= 0 ,0
Exp/Cntr=0.3,0.1

Type RM Length L Ch R = 1 ,3493.3  ,294.3,300,304.4
XS GIS Cut Line= 4
     1708245.407      414549.087      1708351.35      414545.043
     1708582.914      414360.144     1708892.965      414092.723
#Sta/Elev= 30
       0   828.1     7.8  825.17    15.7  824.91    43.2  810.74    82.5  793.98
   141.6  771.68   161.3  762.38   177.1  750.82   181.1  749.25   196.9  749.06
   208.8  743.92   220.6  741.52     268  739.25   287.8  740.27   378.6  735.71
   394.8  731.96   402.4  731.12   409.8  731.54   422.2  737.42   442.1   751.5
   485.8  787.67   533.5  818.31   553.4  829.58   585.2   851.2   597.1  856.84
   668.7  904.62   684.6  913.59   744.2  937.17   787.9  960.12   811.8  974.56
#Mann= 3 , 0 , 0
       0     .08       0   394.8    .045       0   409.8      .1       0
#XS Ineff= 2 , 0
          281.09  748.42
Permanent Ineff=
       F       F
Bank Sta=394.8,409.8
XS Rating Curve= 0 ,0
Exp/Cntr=0.3,0.1

Type RM Length L Ch R = 1 ,3193.3  ,276.6,274,270.9
XS GIS Cut Line= 3
     1708339.871      414795.203     1708710.942      414626.994
     1709077.099      414420.812
#Sta/Elev= 30
       0     812      24  807.34    51.9  799.11    87.9  781.85   135.8  755.61
   151.8  749.31   163.8  746.98   175.8  743.09   227.7  742.52   287.6  736.87
   383.4   734.5   399.9  731.06   407.4  730.21   423.3  731.08   427.2  732.93
   439.1  741.72     455  747.79   474.8  761.06   506.5  791.89   522.4  809.92
   538.2  823.44     570  845.32   597.7  854.22   613.6   861.2   641.3  878.97
   692.8  914.69   752.3  932.84   776.1  942.36     788  945.15   827.6  964.44
#Mann= 3 , 0 , 0
       0     .08       0   399.9    .045       0   423.3      .1       0
Bank Sta=399.9,423.3
XS Rating Curve= 0 ,0
Exp/Cntr=0.3,0.1

Type RM Length L Ch R = 1 ,2919.3  ,341,326,309.7
XS GIS Cut Line= 5
     1708399.055      414988.339     1708532.198      415050.374
     1708841.923      414865.421     1708997.378      414746.118
     1709105.835       414554.51
#Sta/Elev= 30
       0  821.06    11.9  814.36    27.8  807.44    55.6  788.89    83.4  774.13
   111.2  756.86     127  751.91   234.1  747.29   261.8   743.2   345.1  736.38
   436.3  733.48   483.8  733.29   501.3     729   507.6  728.45   523.6   728.6
   527.6  729.64   531.6  732.38   547.6  745.05   563.6  762.78   571.6  769.66
   675.6  830.55   707.5  844.42     735  850.14   750.8  856.06   770.4  867.33
   801.9  890.11   817.6  900.22   841.2  913.07   884.4  928.46   923.8   938.1
#Mann= 3 , 0 , 0
       0     .08       0   501.3    .045       0   523.6      .1       0
Bank Sta=501.3,523.6
XS Rating Curve= 0 ,0
Exp/Cntr=0.3,0.1

Type RM Length L Ch R = 1 ,2593.3  ,264,254.2,246.9
XS GIS Cut Line= 3
      1708927.42      415431.823     1709065.897        415071.7
     1709187.465      414530.445
#Sta/Elev= 30
       0  860.77    27.8   843.5    67.6  824.28   119.3  792.62   123.3   788.9
   127.3  782.24   139.2  757.93   143.2  753.52   155.1  744.65     179  732.92
   218.8  730.35   242.6  731.54     362  730.08   373.9  727.94   381.8  725.85
   393.3  727.27   405.8  729.86   493.6  730.38   509.6  737.42   545.5  746.98
   573.4  759.15   593.4  769.43   601.3  775.48   637.3  792.05   681.2   822.4
     729  850.58     761  861.98   860.8  917.45   904.6  934.98   940.6  947.16
#Mann= 3 , 0 , 0
       0     .08       0   373.9    .045       0   393.3     .08       0
Bank Sta=373.9,393.3
XS Rating Curve= 0 ,0
Exp/Cntr=0.3,0.1

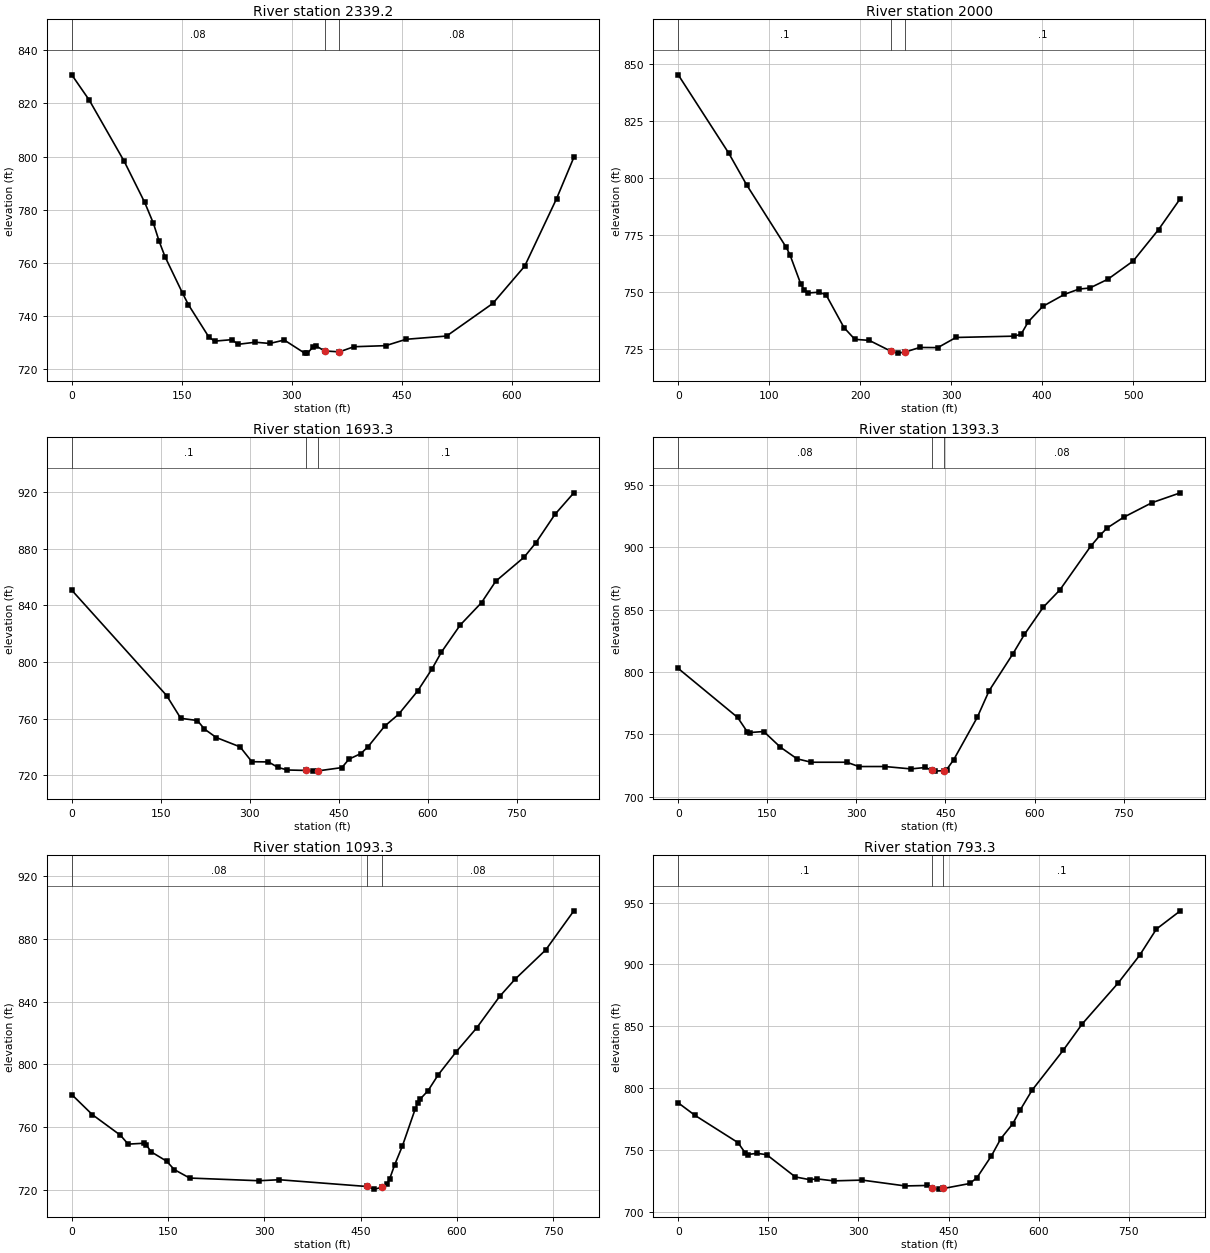
Type RM Length L Ch R = 1 ,2339.2  ,355.5,339.2,319.6
XS GIS Cut Line= 5
      1709367.94      415454.705     1709324.557      415281.174
     1709310.097      415107.642     1709295.771      414930.631
     1709223.331      414794.924
#Sta/Elev= 30
       0   830.8    23.8  821.28    71.6  798.13    99.4  782.71   111.3  774.81
   119.2  767.98   127.2  762.18     151   748.5     159  744.14   186.8  731.98
   194.7  730.41   218.4  730.97   226.4   729.2   250.1     730   269.9  729.54
   289.7  730.82   317.4  725.89   321.3  725.91   329.3  728.31   333.2  728.56
   344.7  726.71   364.8  726.37   384.6   728.3     428  728.71   455.6   731.1
   510.9  732.33     574  744.64   617.4  758.68   660.8  784.09   684.4  799.69
#Mann= 3 , 0 , 0
       0     .08       0   344.7    .045       0   364.8     .08       0
Bank Sta=344.7,364.8
XS Rating Curve= 0 ,0
Exp/Cntr=0.3,0.1

Type RM Length L Ch R = 1 ,2000    ,303.1,306.6,312.9
XS GIS Cut Line= 3
     1709772.848      415098.604      1709588.47      414930.495
     1709346.249      414749.733
#Sta/Elev= 30
       0  845.09    55.4   810.9    75.2  796.95   118.8  769.58   122.8  766.37
   134.7  753.58   138.6   750.9   142.6  749.69   154.5  750.01   162.4  748.93
   182.2  734.53   194.1  729.41   209.9  728.96   233.7  724.23   241.6  723.38
   249.5  723.87   265.4  725.86   285.3  725.79   305.2  730.23   368.8   730.8
   376.8  731.63   384.7  737.08   400.6  743.81   424.5  749.08   440.4  751.39
   452.3  751.86   472.2   755.7     500  763.67   527.9  777.42   551.8  790.97
#Mann= 3 , 0 , 0
       0      .1       0   233.7    .045       0   249.5      .1       0
Bank Sta=233.7,249.5
XS Rating Curve= 0 ,0
Exp/Cntr=0.3,0.1

Type RM Length L Ch R = 1 ,1693.3  ,291.6,300,306.2
XS GIS Cut Line= 3
      1710001.32      415051.466     1709754.586      414726.982
     1709504.958      414365.835
#Sta/Elev= 30
       0  850.69   159.9  776.34   183.8  760.23   211.8  758.69   223.8  752.64
   243.8  746.66   283.8  740.09   303.7   729.6   331.7  729.45   347.7  725.58
   363.7  723.76   395.6  723.44   407.6  722.96   415.1  723.13   455.5  725.45
   467.5  731.41   487.5  735.34   499.4  740.07   527.4  754.59   551.3  763.16
   583.2  779.48   607.2  794.89   623.2  806.85   655.1   826.1     691  841.91
     715  857.02   762.8  873.96   782.8  884.24   814.7  904.13   846.7  919.41
#Mann= 3 , 0 , 0
       0      .1       0   395.6    .045       0   415.1      .1       0
Bank Sta=395.6,415.1
XS Rating Curve= 0 ,0
Exp/Cntr=0.3,0.1

Type RM Length L Ch R = 1 ,1393.3  ,288.8,300,310.3
XS GIS Cut Line= 3
     1710119.231      414970.389      1709975.45      414554.622
     1709832.599      414175.162
#Sta/Elev= 30
       0  802.84     100  763.62     116  752.28     120  751.51     144  752.35
     172  739.83     200   730.5     224  727.76     284  727.76     304  724.32
   347.9  724.34   391.9  722.42   415.9  723.56   427.9  721.28   431.9  720.65
   447.4  721.08   451.8  721.78   463.8  729.76   503.5   763.7   523.4  784.93
   563.2  814.29     583  830.13   614.8  851.94   642.7  865.72   694.3   900.5
   710.2  909.41   722.2  915.25     750  923.83   797.7  935.49   845.4  943.38
#Mann= 3 , 0 , 0
       0     .08       0   427.9    .045       0   447.4     .08       0
Bank Sta=427.9,447.4
XS Rating Curve= 0 ,0
Exp/Cntr=0.3,0.1

Type RM Length L Ch R = 1 ,1093.3  ,289.7,300,311.5
XS GIS Cut Line= 4
     1710202.034       414955.29     1710262.242      414479.929
     1710276.489      414344.944      1710333.21      414187.563
#Sta/Elev= 30
       0  780.66    31.9  767.91    75.9  754.68    87.8  749.03   111.8  749.59
   115.8  748.65   123.8  744.08   147.7  738.18   159.7  732.78   183.7  727.38
   291.5  725.67   323.4   726.3   459.2  722.01   471.2  720.31   483.2  721.38
   491.1   723.6   495.1  726.67   503.1  735.88   515.1  747.85     535  771.39
     539  775.31     543  777.87     555  783.13     571  793.34   598.9  807.95
   630.8  823.21   666.7  843.37   690.6   854.3   738.4  873.01   782.2  897.96
#Mann= 3 , 0 , 0
       0     .08       0   459.2    .045       0   483.2     .08       0
Bank Sta=459.2,483.2
XS Rating Curve= 0 ,0
Exp/Cntr=0.3,0.1

Type RM Length L Ch R = 1 ,793.3   ,431.3,443.6,446.6
XS GIS Cut Line= 3
     1710275.537      414991.116     1710508.423      414630.203
     1710744.391      414299.559
#Sta/Elev= 30
       0  788.17    27.8  778.08    99.4  756.04   111.4  747.77   115.3  746.42
   131.2  747.36   147.2  746.28   194.9  728.29   218.7   726.1   230.7  726.74
   258.5  725.11   306.2  725.74   377.8  721.02   413.6  721.38     422  719.63
   433.5  718.44   441.5  718.96   485.3  722.99   497.2  727.69   521.1  745.18
     537  759.26     557  771.39   568.9  782.15   588.8  798.29   640.6  830.53
   672.5  851.99   732.2  884.98     768  907.42   795.9   928.6   835.7  943.35
#Mann= 3 , 0 , 0
       0      .1       0     422    .045       0   441.5      .1       0
Bank Sta=422,441.5
XS Rating Curve= 0 ,0
Exp/Cntr=0.3,0.1

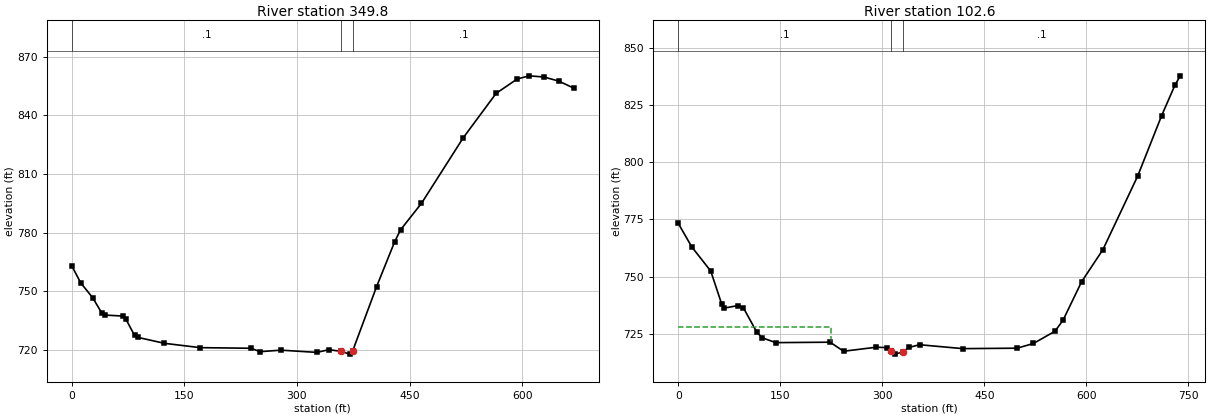
Type RM Length L Ch R = 1 ,349.8   ,247.6,247.2,245.1
XS GIS Cut Line= 2
     1710586.277      415131.141     1711043.605      414643.083
#Sta/Elev= 30
       0  763.04    11.9  754.31    27.9  746.68    39.8     739    43.8  737.85
    67.7  737.32    71.7  736.04    83.6  727.42    87.6  726.45   123.4  723.38
   171.2  721.16   238.9  720.85   250.8   719.1   278.7  719.88   326.5  718.73
   342.4  720.12   358.3   719.3   370.2  717.85   374.2  719.53   406.1  752.44
     430  775.22   437.9  781.42   465.8  794.96   521.5  828.54   565.3  851.26
   593.2  858.55   609.1  860.21     629  859.61   648.9  857.48   668.8  853.89
#Mann= 3 , 0 , 0
       0      .1       0   358.3    .045       0   374.2      .1       0
Bank Sta=358.3,374.2
XS Rating Curve= 0 ,0
Exp/Cntr=0.3,0.1

Type RM Length L Ch R = 1 ,102.6   ,107,102.6,99.1
XS GIS Cut Line= 3
     1710711.003      415319.134     1711086.988      414928.688
     1711025.529      414742.503
#Sta/Elev= 30
       0  773.27    19.9  762.96    47.8  752.38    63.8  738.02    67.8   736.2
    87.7  737.28    95.7  736.36   115.6  725.59   123.6  723.16   143.5  721.08
   223.2  721.27   243.1  717.31     291  719.07   306.9  718.91   313.1  717.54
   318.8  716.05   330.8  717.04   338.8  718.95   354.7  720.16   418.5  718.45
   498.2  718.65   522.1   720.7   553.8  726.05   565.6  730.84     593  747.72
   624.4  761.81   675.4  793.93   710.7  820.42   730.3  833.78   738.1  837.79
#Mann= 3 , 0 , 0
       0      .1       0   313.1    .045       0   330.8      .1       0
#XS Ineff= 2 , 0
          224.31     728
Permanent Ineff=
       F       F
Bank Sta=313.1,330.8
XS Rating Curve= 0 ,0
Exp/Cntr=0.3,0.1

Chan Stop Cuts=-1
Use User Specified Reach Order=0
Composite Channel Slope=5